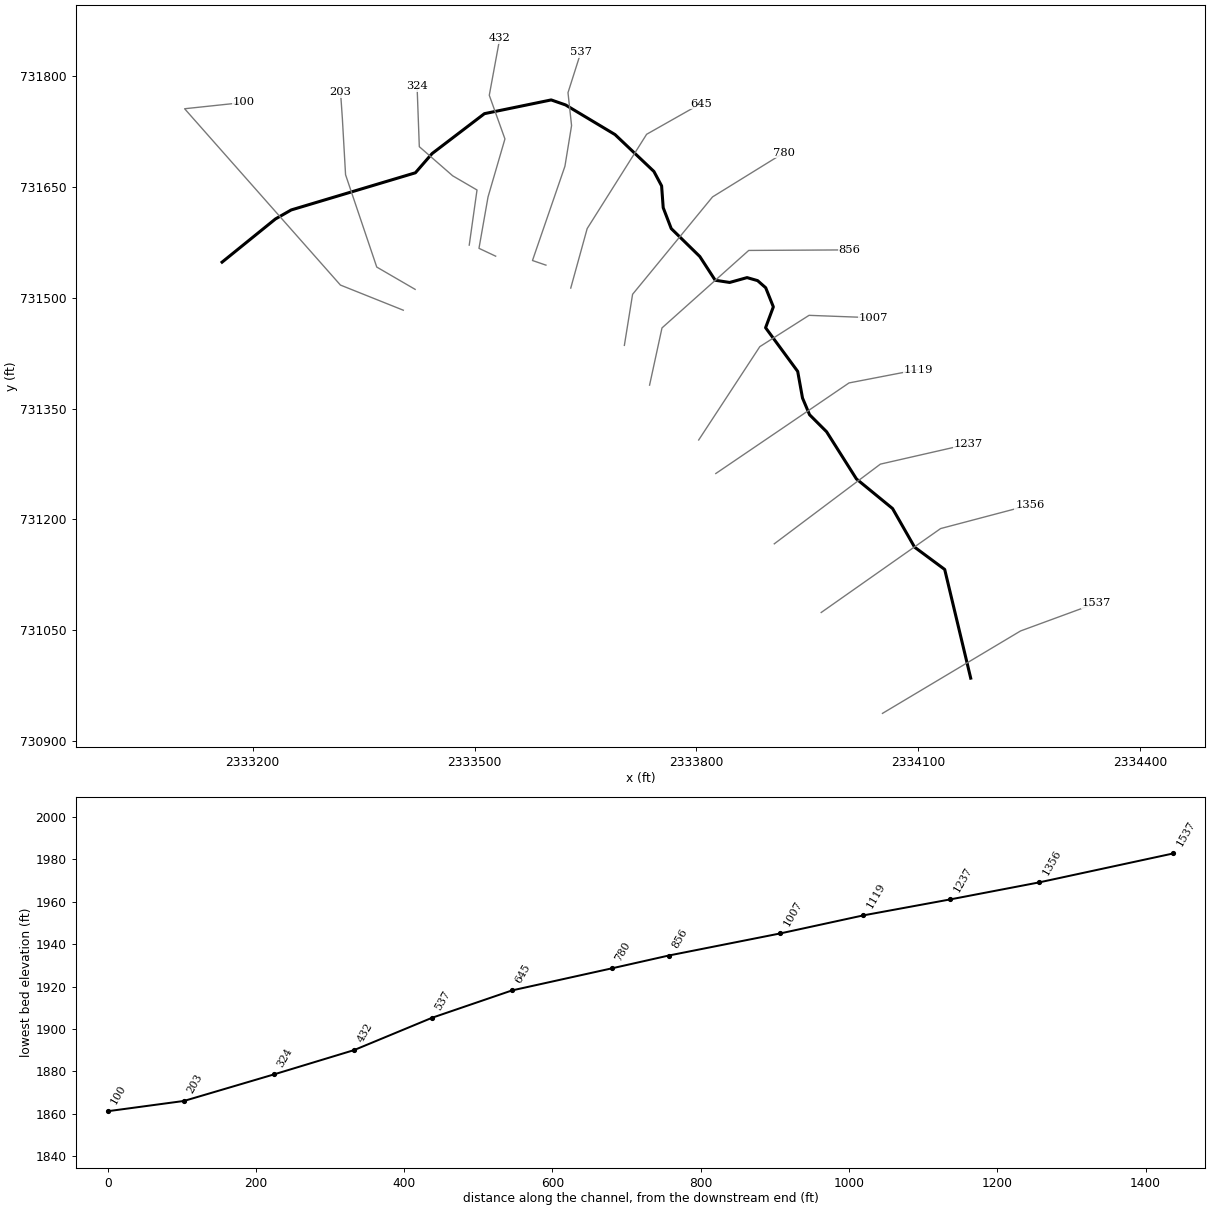
--- SHAVRSFKT1.prj (project) ---

Proj Title=SHAVRSFKT1
Current Plan=p01
Default Exp/Contr=0,0
English Units
Geom File=g01
Flow File=f01
Plan File=p01
BEGIN DESCRIPTION:
----------MODEL BY WOOD PLC 2022----------
AFH study
Randolph County, WV
HEC-RAS Version: RAS 6.2
Vertical Datum: NAVD88
Projection: NAD 1983 StatePlane West Virginia S FIPS 4702 (US Feet)
Terrain: 1-meter LIDAR (FEMA Region III 3DEP collected 2016-2018)
Land Use: 2019 NLCD
Hydrologic Method:
WV SIR2010-5033 regression equations
Additional Model Notes:
None
END DESCRIPTION:
DSS Export Rating Curves= 0
DSS Export Rating Curve Sorted= 0
DSS Export Volume Flow Curves= 0
DXF OffsetX= 0
DXF OffsetY= 0
DXF ScaleX= 0
DXF ScaleY= 0

--- SHAVRSFKT1.p01 (plan) ---

Plan Title=Floodplain
Program Version=6.20
Short Identifier=Floodplain
Geom File=g01
Flow File=f01
Subcritical Flow
K Sum by GR= 0
Std Step Tol= 0.01
Critical Tol= 0.01
Num of Std Step Trials= 20
Max Error Tol= 0.3
Flow Tol Ratio= 0.001
Split Flow NTrial= 30
Split Flow Tol= 0.02
Split Flow Ratio= 0.02
Log Output Level= 0
Friction Slope Method= 1
Unsteady Friction Slope Method= 2
Unsteady Bridges Friction Slope Method= 1
Parabolic Critical Depth
Global Vel Dist= 0 , 0 , 0
Global Log Level= 0
CheckData=True
Encroach Param=-1 ,0,0, 0
Mapping Interval=1HOUR
Computation Time Step Use Courant=        0
Computation Time Step Use Time Series=    0
Computation Time Step Count To Double=0
Computation Time Step Max Doubling=0
Computation Time Step Max Halving=0
Computation Time Step Residence Courant=0
Run HTab= 0
Run UNet= 0
Run Sediment= 0
Run PostProcess= 0
Run WQNet= 0
Run RASMapper=-1
UNET Theta= 0
UNET Theta Warmup= 0
UNET ZTol= 0
UNET ZSATol= 0
UNET MxIter= 0
UNET Max Iter WO Improvement= 0
UNET MaxInSteps= 0
UNET DtIC= 0
UNET DtMin= 0
UNET MaxCRTS= 0
UNET WFStab= 0
UNET SFStab= 0
UNET WFX= 1
UNET SFX= 1
UNET Gravity=32.174
UNET 1D Methodology=Finite Difference
UNET DSS MLevel= 1
UNET Pardiso=0
UNET DZMax Abort= 0
UNET Use Existing IB Tables= 0
UNET Froude Reduction=False
UNET Froude Limit= 0
UNET Froude Power= 0
UNET D1 Cores= 0
UNET WindReference=Eulerian
UNET WindDragFormulation=Hsu (1988)
UNET D2 Coriolis=0
UNET D2 Cores= 0
UNET D2 Theta= 1
UNET D2 Theta Warmup= 1
UNET D2 Z Tol= 0.01
UNET D2 Volume Tol= 0.01
UNET D2 Max Iterations= 20
UNET D2 Equation= 0
UNET D2 RampUpFraction=0.1
UNET D2 TimeSlices= 1
UNET D2 Turbulence Formulation=Non-Conservative (original)
UNET D2 Eddy Viscosity=0.3
UNET D2 Transverse Eddy Viscosity=0.1
UNET D2 Smagorinsky Mixing=0
UNET D2 BCVolumeCheck=0
UNET D2 Cores=0
UNET D2 SolverType=PARDISO (Direct)
UNET D2 Minimum Iterations= 2147483647
UNET D2 Maximum Iterations= 2147483647
UNET D2 Restart Number= 10
UNET D2 Relaxation Coeff=1.3
UNET D2 SOR Precondition Iterations= 10
UNET D2 ILUT Maximum Fill= 8
UNET D2 ILUT Tolerance=1E-08
UNET D1D2 MaxIter= 0
UNET D1D2 ZTol=0.01
UNET D1D2 QTol=0.1
UNET D1D2 MinQTol=1
Write IC File= 0
Write IC File at Fixed DateTime=0
Write IC File at Sim End=0
Echo Input=False
Echo Parameters=False
Echo Output=False
Write Detailed= 0
HDF Write Warmup=0
HDF Write Time Slices=0
HDF Flush=0
HDF Compression= 1
HDF Chunk Size= 1
HDF Spatial Parts= 1
HDF Use Max Rows=0
HDF Fixed Rows= 1
Calibration Method= 0
Calibration Iterations= 20
Calibration Max Change=0.05
Calibration Tolerance=0.2
Calibration Maximum=1.5
Calibration Minimum=0.5
Calibration Optimization Method= 1
WQ AD Non Conservative
WQ ULTIMATE=-1
WQ Max Comp Step=1HOUR
WQ Output Interval=15MIN
WQ Output Selected Increments= 0
WQ Output face flow=0
WQ Output face velocity=0
WQ Output face area=0
WQ Output face dispersion=0
WQ Output cell volume=0
WQ Output cell surface area=0
WQ Output cell continuity=0
WQ Output cumulative cell continuity=0
WQ Output face conc=0
WQ Output face dconc_dx=0
WQ Output face courant=0
WQ Output face peclet=0
WQ Output face adv mass=0
WQ Output face disp mass=0
WQ Output cell mass=0
WQ Output cell source sink temp=0
WQ Output nsm pathways=0
WQ Output nsm derived pathways=0
WQ Create Restart=0
WQ Fixed Restart=0
WQ System Summary=0
WQ Write To DSS=0
Sorting and Armoring Iterations= 10
XS Update Threshold= 0.02
Bed Roughness Predictor= 0
Hydraulics Update Threshold= 0.02
Energy Slope Method= 1
Volume Change Method= 1
Sediment Retention Method= 0
Sediment TS Multiplier= 1
Warm Up Method= 0
XS Weighting Method= 0
Number of US Weighted Cross Sections= 1
Number of DS Weighted Cross Sections= 1
Upstream XS Weight=0
Main XS Weight=1
Downstream XS Weight=0
Number of DS XS's Weighted with US Boundary= 1
Upstream Boundary Weight= 1
Weight of XSs Associated with US Boundary= 0
Number of US XS's Weighted with DS Boundary= 1
Downstream Boundary Weight= 0.5
Weight of XSs Associated with DS Boundary= 0.5
Percentile Method= 0
Sediment Output Level= 3
Mass or Volume Output= 0
Output Increment Type= 1
Profile and TS Output Increment= 1
Transport Output Increment 1
XS Output Flag= 0
XS Output Increment= 10
Read HDF5 Sediment Hotstart= 0
Sediment Hotstart Type= 0
Write Gradation File= 0
Read Gradation Hotstart= 0
Write HDF5 File= 1
Write Binary Output= 1
Write DSS Sediment File= 0
DSS Sediment Output Type= 1
SV Curve= 0
Specific Gage Flag= 0
Subcell Erosion Methods= 0
Subcell Deposition Methods= 0
Advection Scheme= 1
Matrix Solver= 0
Implicit Weighting Factor= 1
Maximum Outer Loop Convergence Iterations= 5
Convergence Maximum Absolute= 0.001
Convergence RMSE= 0.0001
Grain Fractions Max Abs Error= 0.001
Max Subgrid Regions= 1
Max Subgrid Length Scale= 3.402823E+38
Initial Layer Thickness= 3.402823E+38
Min Layer Thickness= 3.402823E+38
Max Layer Thickness= 3.402823E+38
Number of Layers= 5

--- SHAVRSFKT1.f01 (steady flow) ---

Flow Title=Flow
Program Version=6.20
Number of Profiles= 1
Profile Names=P100yr
River Rch & RM=SHAVRSFKT1,Main,1537
     379
Boundary for River Rch & Prof#=SHAVRSFKT1,Main            , 1
Up Type= 0
Dn Type= 3
Dn Slope=0.04703
DSS Import GetInterval= 0
DSS Import GetPeak= 0
DSS Import FillOption= 0

--- SHAVRSFKT1.g01 (geometry) ---

Geom Title=Geometry
Program Version=6.20

River Reach=SHAVRSFKT1      ,Main
Reach XY= 30
2334170.85098619730985.421995397     2334135.685       731132.41
     2334094.932      731162.585     2334065.175      731214.773
     2334016.328      731254.805     2333975.963      731318.608
      2333952.96      731341.611     2333943.411       731364.18
     2333936.901      731400.2052333893.47828594731459.274924173
2333903.96964614731487.4951500952333893.62700635731513.335251197
2333882.69198993731522.9487998932333868.41807427731527.038570316
2333844.89932007731520.484060554     2333825.355      731523.469
     2333804.522      731555.587     2333765.894      731593.347
     2333755.043      731621.559     2333752.873      731651.073
     2333742.456      731670.604     2333689.888      731720.461
      2333623.04      731760.518     2333603.567      731767.302
     2333513.289      731748.7292333442.48549282731694.737564584
2333419.96683727731668.782291897     2333252.029      731618.534
     2333230.737      731606.368     2333158.534      731547.952

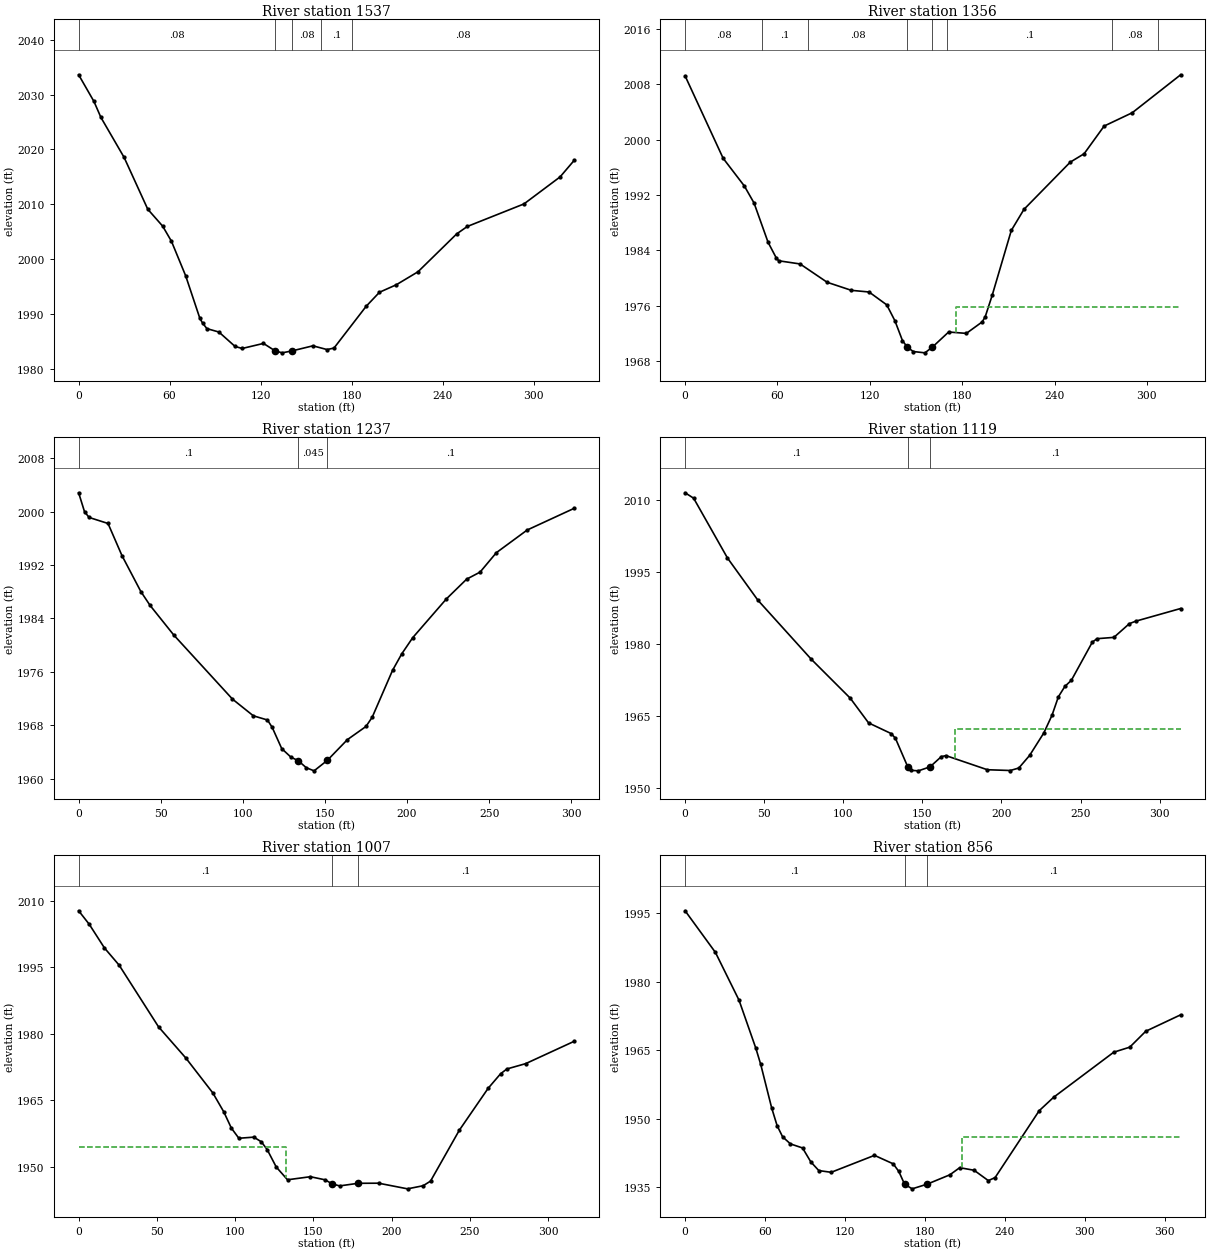
Type RM Length L Ch R = 1 ,1537    ,179.2,180.9,181.3
XS GIS Cut Line= 3
2334051.54369607730937.7915528582334238.27978705731049.255750901
2334340.90899873731086.951342651
#Sta/Elev= 30
       0 2033.63    10.1 2028.76    14.7 2025.84      30 2018.54    45.6 2009.08
    55.4    2006    61.2 2003.24    70.6 1996.92    79.9  1989.2    81.7 1988.31
    84.6 1987.28    92.5 1986.66   103.2 1984.02   107.9 1983.66   121.9 1984.58
  129.471983.238   134.2 1982.86   140.5  1983.2   154.5 1984.14   163.8 1983.46
   168.4 1983.73   189.6 1991.35   198.4 1993.92   209.5 1995.29   223.8 1997.66
   249.3 2004.57   256.3 2005.93   293.7 2010.05   317.5 2014.98   326.8    2018
#Mann= 5 ,-1,0
       0     .08       0  129.47    .045       0   140.5     .08       0
     160      .1       0     180     .08       0
Bank Sta=129.47,140.5
XS Rating Curve= 0 ,0
Exp/Cntr(USF)=0,0
Exp/Cntr=0.3,0.1

Type RM Length L Ch R = 1 ,1356    ,119.3,119.8,119.7
XS GIS Cut Line= 3
2333968.67393631731074.2112038522334130.15342767731187.697911975
2334250.60829476731219.482401794
#Sta/Elev= 30
       0  2009.2    24.7  1997.3    38.5 1993.29    44.8 1990.83    53.9 1985.16
    59.2 1982.91    60.8 1982.49    74.7 1982.03    92.3 1979.38     108 1978.22
   119.5 1977.98     131 1976.12   136.3 1973.82   141.2 1970.96   144.3 1970.02
   148.2 1969.38   155.8 1969.19   160.7 1970.03   171.2  1972.2   182.7    1972
     193 1973.66     195 1974.43   199.5 1977.51   211.9 1986.87   220.1 1989.91
   250.2 1996.74   259.2 1997.95   272.2 2001.95   290.5 2003.88   321.9 2009.36
#Mann= 8 ,-1,0
       0     .08       0      50      .1       0      80     .08       0
   144.3    .045       0   160.7     .08       0     170      .1       0
  277.37     .08       0  307.37      .1       0
#XS Ineff= 2 , 0
                          176.14         1975.86
Permanent Ineff=
       F       F
Bank Sta=144.3,160.7
XS Rating Curve= 0 ,0
Exp/Cntr(USF)=0,0
Exp/Cntr=0.3,0.1

Type RM Length L Ch R = 1 ,1237    ,117.6,117.5,117
XS GIS Cut Line= 3
2333905.25267124731167.0781068562334048.69998353731274.827771662
2334168.01445336731302.058964664
#Sta/Elev= 30
       0 2002.84     3.6 1999.99     6.4 1999.14    17.9 1998.24    26.4 1993.42
    37.9 1988.03    43.5 1985.96    57.9 1981.53    93.7 1971.91   106.4 1969.41
     115 1968.78   117.9 1967.67   123.7 1964.49   129.3 1963.21   133.7 1962.69
   138.7 1961.62   143.4 1961.16  151.471962.733   163.7 1965.84     175 1967.81
   178.8  1969.2   191.2 1976.23   196.8  1978.7   203.5 1981.13     224 1986.94
   236.3 1989.89   244.5 1990.95   254.4 1993.86   273.2 1997.26   301.8 2000.51
#Mann= 3 ,-1,0
       0      .1       0   133.7    .045       0  151.47      .1       0
Bank Sta=133.7,151.47
XS Rating Curve= 0 ,0
Exp/Cntr(USF)=0,0
Exp/Cntr=0.3,0.1

Type RM Length L Ch R = 1 ,1119    ,112.3,112,112.2
BEGIN DESCRIPTION:
Disconnected without IFA
END DESCRIPTION:
XS GIS Cut Line= 4
2333826.15687506731262.1271279042333920.20090638731325.977889749
2334006.28281243 731384.613390972334100.02288129731402.696487055
#Sta/Elev= 30
       0 2011.48     5.4 2010.35    26.8  1997.9      46 1989.13    79.8 1976.82
   104.4 1968.73     116 1963.58   130.4 1961.34     133 1960.36   140.7 1954.49
   142.7 1953.71   147.5  1953.6   154.9 1954.44     162 1956.56   164.9 1956.77
   191.1 1953.83   205.6 1953.67     211 1954.19   217.8  1956.8   226.8 1961.49
     232 1965.19     236 1969.01   240.1 1971.17   244.2 1972.44   257.5 1980.41
   260.5 1981.11   271.1 1981.38   280.9 1984.24   284.9 1984.75   313.3 1987.39
#Mann= 3 ,-1,0
       0      .1       0   140.7    .045       0   154.9      .1       0
#XS Ineff= 2 , 0
                          170.58         1962.31
Permanent Ineff=
       F       F
Bank Sta=140.7,154.9
XS Rating Curve= 0 ,0
Exp/Cntr(USF)=0,0
Exp/Cntr=0.3,0.1

Type RM Length L Ch R = 1 ,1007    ,147,150.6,150.1
XS GIS Cut Line= 4
2333803.04163596731307.5047349562333885.64957457 731433.65734687
2333952.25290956731476.0264693622334039.14598093731472.759170768
#Sta/Elev= 30
       0 2007.69     6.8 2004.64    16.5 1999.32    25.9 1995.44    51.1 1981.54
    68.5 1974.54    85.8 1966.66    92.8 1962.39    97.6 1958.76   102.4 1956.47
     112 1956.72   116.8 1955.66   120.5 1953.92   126.3 1949.99   133.5 1947.12
   148.1 1947.81   157.4 1947.12   162.11946.194   166.8 1945.74   178.61946.328
   191.7 1946.35   210.2 1945.08   220.2 1945.78   224.9 1946.82   243.3 1958.28
   261.7 1967.71   269.7    1971   273.7 1972.07   285.7 1973.27   316.7  1978.3
#Mann= 3 ,-1,0
       0      .1       0   162.1    .045       0   178.6      .1       0
#XS Ineff= 2 , 0
          132.56 1954.48
Permanent Ineff=
       F       F
Bank Sta=162.1,178.6
XS Rating Curve= 0 ,0
Exp/Cntr(USF)=0,0
Exp/Cntr=0.3,0.1

Type RM Length L Ch R = 1 ,856     ,76.5,76.7,78.7
XS GIS Cut Line= 4
2333736.61418133731381.6451532362333753.39912374731458.990652923
2333870.67012618731563.7860168072334006.34604283731564.516890579
#Sta/Elev= 30
       0 1995.51    22.8 1986.38    40.5 1975.93    53.1 1965.43    56.8 1961.86
      65 1952.35    69.1 1948.46    73.2 1946.03    79.1 1944.47    88.2 1943.58
    94.4 1940.53   100.4 1938.63   109.7 1938.25   142.2 1941.96   156.3  1940.1
   160.5 1938.43  164.77 1935.66   170.5 1934.63   181.8 1935.66   198.8  1937.7
   206.2 1939.26     217  1938.7   227.7 1936.43   232.8  1937.1   265.9 1951.74
   276.7 1954.67   321.9 1964.55   333.9 1965.65   345.9 1969.13   372.1 1972.73
#Mann= 3 ,0,0
       0      .1       0  164.77    .045       0   181.8      .1       0
#XS Ineff= 2 , 0
                          207.65         1946.05
Permanent Ineff=
       F       F
Bank Sta=164.77,181.8
XS Rating Curve= 0 ,0
Exp/Cntr(USF)=0,0
Exp/Cntr=0.3,0.1

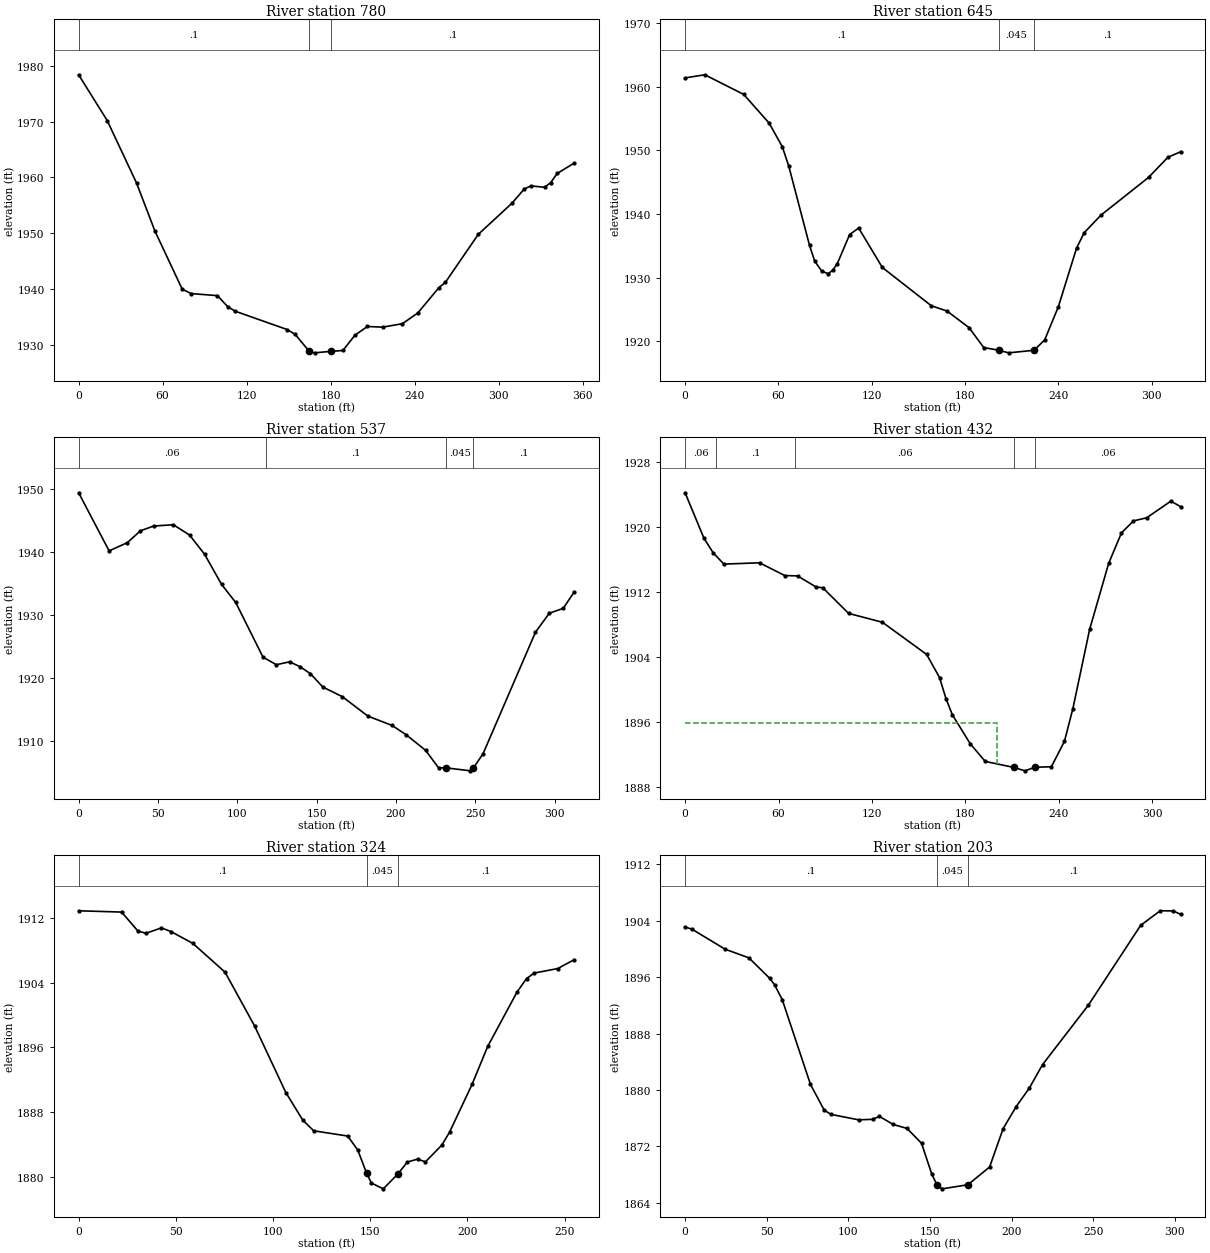
Type RM Length L Ch R = 1 ,780     ,133.6,134.6,139.2
XS GIS Cut Line= 4
2333702.52872195731435.4090509532333713.63905297731504.481630831
 2333821.7612538731636.1689267172333918.45064149731695.949011188
#Sta/Elev= 30
       0 1978.38    20.4 1970.19    41.4 1958.98    54.5 1950.39      74 1939.98
    80.3  1939.2    99.2 1938.82   106.4 1936.87   111.8 1936.04     149 1932.75
   154.7 1931.88  164.791928.843   168.5 1928.58   180.3 1928.85   188.8    1929
   197.3 1931.72   206.3  1933.3   217.2 1933.18   231.3  1933.8   242.3 1935.72
   257.3 1940.24     262 1941.21   285.5  1949.8   309.7 1955.41   318.3 1957.92
   323.1 1958.48   332.9 1958.23   337.2 1959.06   341.9 1960.71     354 1962.56
#Mann= 3 ,-1,0
       0      .1       0  164.79    .045       0   180.3      .1       0
Bank Sta=164.79,180.3
XS Rating Curve= 0 ,0
Exp/Cntr(USF)=0,0
Exp/Cntr=0.3,0.1

Type RM Length L Ch R = 1 ,645     ,105.9,107.8,116.6
BEGIN DESCRIPTION:
Structure XS 4
END DESCRIPTION:
XS GIS Cut Line= 4
2333630.03445094731512.9018819072333652.21336393731593.300441501
2333732.61192352731720.8291912022333806.07957281731762.414653061
#Sta/Elev= 30
       0 1961.38    12.7 1961.87    37.7 1958.78      54 1954.28    62.5 1950.56
    66.7 1947.47      80 1935.05    83.3 1932.59      88 1930.96      92 1930.61
    94.9 1931.14    97.8 1932.15   105.8 1936.76   111.6 1937.78   126.8 1931.58
   158.3 1925.56   168.4 1924.73   182.6 1922.11     192 1918.99   201.5 1918.58
     208 1918.16  224.32 1918.56   231.2 1920.19     240 1925.42   251.7 1934.63
   256.6 1937.04   267.3 1939.79     298 1945.74   310.4  1948.9   318.6 1949.77
#Mann= 3 ,0,0
       0      .1       0   201.5    .045       0  224.32      .1       0
Bank Sta=201.5,224.32
XS Rating Curve= 0 ,0
Exp/Cntr(USF)=0,0
Exp/Cntr=0.3,0.1

Type RM Length L Ch R = 1 ,537     ,103.8,105.3,105.2
BEGIN DESCRIPTION:
Structure XS 3
END DESCRIPTION:
XS GIS Cut Line= 6
2333596.45527939731543.9161859382333578.27053837731550.162938124
2333622.15103688 731677.63828714 2333631.1289905731732.599083296
2333626.29567251731777.0946457522333643.61033418731831.499862768
#Sta/Elev= 30
       0 1949.45    19.2 1940.22    30.7 1941.52    38.9  1943.4    47.2 1944.16
    59.7 1944.37    69.9 1942.73    79.4 1939.67    90.1 1934.88      99 1932.01
   116.2 1923.32   124.6 1922.12     133 1922.58   139.7 1921.78   146.1 1920.69
   153.9 1918.57   166.2 1917.04   182.3 1913.95   197.6 1912.46   206.6 1910.95
   218.7  1908.5   226.8 1905.74231.48161905.729   246.9 1905.25248.72161905.667
   254.9 1907.98   287.9 1927.28   296.6  1930.3   305.4 1931.08   312.3 1933.67
#Mann= 4 ,-1,0
       0     .06       0  117.92      .1       0231.4816    .045       0
248.7216      .1       0
Bank Sta=231.4816,248.7216
XS Rating Curve= 0 ,0
Exp/Cntr(USF)=0,0
Exp/Cntr=0.3,0.1

Type RM Length L Ch R = 1 ,432     ,104.5,108.1,111.9
BEGIN DESCRIPTION:
Structure XS 2
END DESCRIPTION:
XS GIS Cut Line= 6
2333528.47606687731556.0327496522333505.92542226731566.623742952
2333518.18738223731636.1689267172333541.02715647731714.543170897
2333519.85785458731773.5980536722333534.06021961731850.586575759
#Sta/Elev= 30
       0  1924.2    12.1 1918.61      18 1916.82    24.9 1915.42    47.8 1915.58
      64 1914.01    72.2 1913.97    84.1  1912.6    88.4 1912.51     105 1909.35
   126.7 1908.26   155.1  1904.3   163.4 1901.45   167.5 1898.87   171.6 1896.88
     183 1893.33   192.7 1891.13211.24411890.384   218.2 1889.97224.61411890.415
   235.2 1890.47   243.6 1893.61     249 1897.63   259.8 1907.41     272 1915.52
   280.2 1919.26   287.9 1920.74   296.4 1921.12   311.9 1923.17   318.2 1922.49
#Mann= 5 ,-1,0
       0     .06       0      20      .1       0   70.61     .06       0
211.2441    .045       0224.6141     .06       0
#XS Ineff= 2 , 0
           200.4 1895.83
Permanent Ineff=
       F       F
Bank Sta=211.2441,224.6141
XS Rating Curve= 0 ,0
Exp/Cntr(USF)=0,0
Exp/Cntr=0.3,0.1

Type RM Length L Ch R = 1 ,324     ,124.2,121.2,115.3
BEGIN DESCRIPTION:
Structure XS 1
END DESCRIPTION:
XS GIS Cut Line= 5
 2333492.7502808731570.9630634292333503.26575553731645.508144738
2333470.41972917 731664.653480342333425.24918915731704.075142479
2333422.22952716731785.627056205
#Sta/Elev= 30
       0 1912.93    22.1 1912.77    30.5 1910.42    34.6 1910.14    42.6 1910.81
    47.5 1910.36    58.8 1908.88    75.3 1905.33    90.5 1898.67   106.6 1890.41
   115.3    1887   120.9 1885.68   138.4 1885.03   143.6 1883.29   148.1 1880.44
   150.6 1879.21   156.7 1878.49   164.1  1880.3   169.1 1881.81   174.4 1882.17
   178.4 1881.83   186.9 1883.93   190.8 1885.51   202.4 1891.44   210.4 1896.12
   225.5 1902.86   230.4 1904.54   234.4 1905.22   246.4 1905.77   254.9 1906.87
#Mann= 3 ,-1,0
       0      .1       0   148.1    .045       0   164.1      .1       0
Bank Sta=148.1,164.1
XS Rating Curve= 0 ,0
Exp/Cntr(USF)=0,0
Exp/Cntr=0.3,0.1

Type RM Length L Ch R = 1 ,203     ,101.2,103,106.9
XS GIS Cut Line= 5
2333419.58764157731511.1506590352333367.68675409731541.306857545
2333325.51827371 731666.165902122333321.17519764731742.556281886
2333318.75271993731777.660703205
#Sta/Elev= 30
       0 1903.09       4 1902.84    24.5 1899.97    39.1 1898.74    51.8 1895.84
    54.8 1894.92    59.5 1892.81    76.8 1880.78    85.2 1877.13    89.4 1876.53
   106.3 1875.76   114.8 1875.83     119 1876.25   127.4 1875.11   135.9 1874.54
   144.8 1872.44   151.1 1868.05   154.2 1866.57   157.4 1865.97   173.2 1866.55
   186.5 1869.07   194.8 1874.52   202.8 1877.65   210.9 1880.29   218.9 1883.59
   246.9    1892     279 1903.35     291 1905.42     299  1905.4   303.5 1904.91
#Mann= 3 ,-1,0
       0      .1       0   154.2    .045       0   173.2      .1       0
Bank Sta=154.2,173.2
XS Rating Curve= 0 ,0
Exp/Cntr(USF)=0,0
Exp/Cntr=0.3,0.1

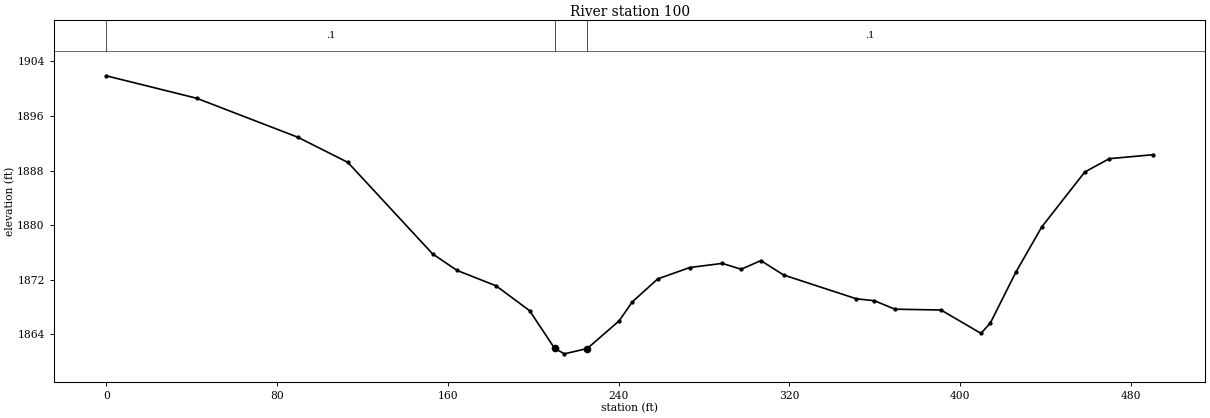
Type RM Length L Ch R = 1 ,100     ,,,
XS GIS Cut Line= 4
2333403.58177914731482.9534752922333318.57716531731516.957269388
2333107.87749189731755.3805840462333187.96963291731763.886059511
#Sta/Elev= 30
       0  1901.9    42.4  1898.6    89.8 1892.88   113.2 1889.19   152.9 1875.76
   164.3 1873.35   182.6 1871.09   198.3 1867.44     210 1861.92   214.6 1861.11
   225.3 1861.89   240.2 1865.94   246.4 1868.73   258.3  1872.1   273.3 1873.77
   288.5 1874.38   297.4 1873.52   306.6 1874.79   317.3 1872.67   351.3 1869.19
   359.8  1868.9   369.4 1867.66     391 1867.54   409.7 1864.11   414.1 1865.64
     426 1873.07   438.2 1879.74   458.3 1887.78   469.8 1889.74   490.3 1890.32
#Mann= 3 ,-1,0
       0      .1       0     210    .045       0   225.3      .1       0
Bank Sta=210,225.3
XS Rating Curve= 0 ,0
Exp/Cntr(USF)=0,0
Exp/Cntr=0.3,0.1
LCMann Table=0

Chan Stop Cuts=-1
Use User Specified Reach Order=0
Composite Channel Slope=5